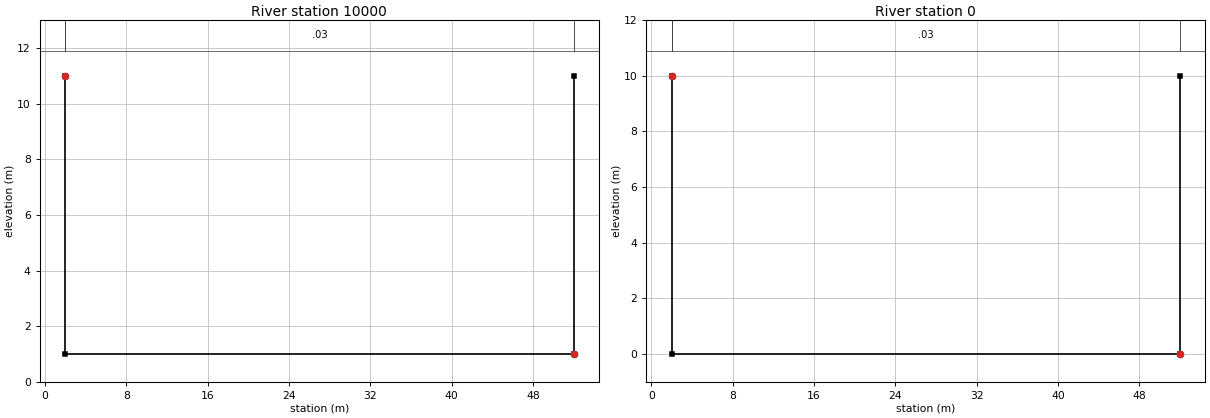
--- run_1_c6.prj (project) ---

Proj Title=run_1_c6
Current Plan=p01
Default Exp/Contr=0.3,0.1
SI Units
Geom File=g01
Unsteady File=u01
Plan File=p01
Y Axis Title=Elevation
X Axis Title(PF)=Main Channel Distance
X Axis Title(XS)=Station
BEGIN DESCRIPTION:
END DESCRIPTION:
DSS File=dss
DSS Export Rating Curves= 0
DSS Export Rating Curve Sorted= 0
DSS Export Volume Flow Curves= 0
DXF OffsetX= 0
DXF OffsetY= 0
DXF ScaleX= 1
DXF ScaleY= 10

--- run_1_c6.p01 (plan) ---

Plan Title=Plan_1
Program Version=5.05
Short Identifier=P_1
Simulation Date=08JUN2020,1200,23JUN2020,1200
Geom File=g01
Flow File=u01
Subcritical Flow
K Sum by GR= 0
Std Step Tol= 0.003
Critical Tol= 0.003
Num of Std Step Trials= 20
Max Error Tol= 0.1
Flow Tol Ratio= 0.001
Split Flow NTrial= 30
Split Flow Tol= 0.006
Split Flow Ratio= 0.02
Log Output Level= 0
Friction Slope Method= 1
Unsteady Friction Slope Method= 2
Unsteady Bridges Friction Slope Method= 1
Parabolic Critical Depth
Global Vel Dist= 0 , 0 , 0
Global Log Level= 0
CheckData=True
Encroach Param=-1 ,0,0, 0
BEGIN DESCRIPTION:
first run with stage hydrograph as u/s bc.
END DESCRIPTION:
Computation Interval=1MIN
Output Interval=1HOUR
Instantaneous Interval=1HOUR
Mapping Interval=1HOUR
Computation Time Step Use Courant=        0
Computation Time Step Use Time Series=    0
Computation Time Step Count To Double=0
Computation Time Step Max Doubling=0
Computation Time Step Max Halving=0
Computation Time Step Residence Courant=0
Run HTab=-1
Run UNet=-1
Run Sediment= 0
Run PostProcess=-1
Run WQNet= 0
Run RASMapper= 0
UNET Theta= 1
UNET Theta Warmup= 1
UNET ZTol= 0.06
UNET ZSATol= 0.06
UNET MxIter= 30
UNET Max Iter WO Improvement= 0
UNET MaxInSteps= 0
UNET DtIC= 0
UNET DtMin= 0
UNET MaxCRTS= 20
UNET WFStab= 2
UNET SFStab= 1
UNET WFX= 1
UNET SFX= 1
UNET 1D Methodology=Finite Difference
UNET DSS MLevel= 4
UNET Pardiso=0
UNET DZMax Abort= 30
UNET Use Existing IB Tables=-1
UNET Froude Reduction=False
UNET Froude Limit= 0.8
UNET Froude Power= 4
UNET D1 Cores= 0
UNET D2 Coriolis=0
UNET D2 Cores= 0
UNET D2 Theta= 1
UNET D2 Theta Warmup= 1
UNET D2 Z Tol= 0.003
UNET D2 Volume Tol= 0.003
UNET D2 Max Iterations= 20
UNET D2 Equation= 0
UNET D2 RampUpFraction=0.1
UNET D2 TimeSlices= 1
UNET D2 BCVolumeCheck=0
UNET D1D2 MaxIter= 0
UNET D1D2 ZTol=0.003
UNET D1D2 QTol=0.1
UNET D1D2 MinQTol=0.03
DSS File=dss
Write IC File= 0
Write IC File at Fixed DateTime=0
Write IC File at Sim End=0
Echo Input=False
Echo Parameters=False
Echo Output=False
Write Detailed= 0
Computation Level Output=True
HDF Write Warmup=0
HDF Write Time Slices=0
HDF Flush=0
HDF Face Node Velocities=0
HDF Compression= 1
HDF Chunk Size= 1
HDF Spatial Parts= 1
HDF Use Max Rows=0
HDF Fixed Rows= 1
Stage Flow Hydrograph=river-1         ,reach-1         ,10000
Stage Flow Hydrograph=river-1         ,reach-1         ,9900.00*
Stage Flow Hydrograph=river-1         ,reach-1         ,9800.00*
Stage Flow Hydrograph=river-1         ,reach-1         ,9700.00*
Stage Flow Hydrograph=river-1         ,reach-1         ,9600.00*
Stage Flow Hydrograph=river-1         ,reach-1         ,9500.00*
Stage Flow Hydrograph=river-1         ,reach-1         ,9400.00*
Stage Flow Hydrograph=river-1         ,reach-1         ,9300.00*
Stage Flow Hydrograph=river-1         ,reach-1         ,9200.00*
Stage Flow Hydrograph=river-1         ,reach-1         ,9100.00*
Stage Flow Hydrograph=river-1         ,reach-1         ,9000.00*
Stage Flow Hydrograph=river-1         ,reach-1         ,8900.00*
Stage Flow Hydrograph=river-1         ,reach-1         ,8800.00*
Stage Flow Hydrograph=river-1         ,reach-1         ,8700.00*
Stage Flow Hydrograph=river-1         ,reach-1         ,8600.00*
Stage Flow Hydrograph=river-1         ,reach-1         ,8500.00*
Stage Flow Hydrograph=river-1         ,reach-1         ,8400.00*
Stage Flow Hydrograph=river-1         ,reach-1         ,8300.00*
Stage Flow Hydrograph=river-1         ,reach-1         ,8200.00*
Stage Flow Hydrograph=river-1         ,reach-1         ,8100.00*
Stage Flow Hydrograph=river-1         ,reach-1         ,8000.00*
Stage Flow Hydrograph=river-1         ,reach-1         ,7900.00*
Stage Flow Hydrograph=river-1         ,reach-1         ,7800.00*
Stage Flow Hydrograph=river-1         ,reach-1         ,7700.00*
Stage Flow Hydrograph=river-1         ,reach-1         ,7600.00*
Stage Flow Hydrograph=river-1         ,reach-1         ,7500.00*
Stage Flow Hydrograph=river-1         ,reach-1         ,7400.00*
Stage Flow Hydrograph=river-1         ,reach-1         ,7300.00*
Stage Flow Hydrograph=river-1         ,reach-1         ,7200.00*
Stage Flow Hydrograph=river-1         ,reach-1         ,7100.00*
Stage Flow Hydrograph=river-1         ,reach-1         ,7000.00*
Stage Flow Hydrograph=river-1         ,reach-1         ,6900.00*
Stage Flow Hydrograph=river-1         ,reach-1         ,6800.00*
Stage Flow Hydrograph=river-1         ,reach-1         ,6700.00*
Stage Flow Hydrograph=river-1         ,reach-1         ,6600.00*
Stage Flow Hydrograph=river-1         ,reach-1         ,6500.00*
Stage Flow Hydrograph=river-1         ,reach-1         ,6400.00*
Stage Flow Hydrograph=river-1         ,reach-1         ,6300.00*
Stage Flow Hydrograph=river-1         ,reach-1         ,6200.00*
Stage Flow Hydrograph=river-1         ,reach-1         ,6100.00*
Stage Flow Hydrograph=river-1         ,reach-1         ,6000.00*
Stage Flow Hydrograph=river-1         ,reach-1         ,5900.00*
Stage Flow Hydrograph=river-1         ,reach-1         ,5800.00*
Stage Flow Hydrograph=river-1         ,reach-1         ,5700.00*
Stage Flow Hydrograph=river-1         ,reach-1         ,5600.00*
Stage Flow Hydrograph=river-1         ,reach-1         ,5500.00*
Stage Flow Hydrograph=river-1         ,reach-1         ,5400.00*
Stage Flow Hydrograph=river-1         ,reach-1         ,5300.00*
Stage Flow Hydrograph=river-1         ,reach-1         ,5200.00*
Stage Flow Hydrograph=river-1         ,reach-1         ,5100.00*
Stage Flow Hydrograph=river-1         ,reach-1         ,5000.00*
Stage Flow Hydrograph=river-1         ,reach-1         ,4900.00*
Stage Flow Hydrograph=river-1         ,reach-1         ,4800.00*
Stage Flow Hydrograph=river-1         ,reach-1         ,4700.00*
Stage Flow Hydrograph=river-1         ,reach-1         ,4600.00*
Stage Flow Hydrograph=river-1         ,reach-1         ,4500.00*
Stage Flow Hydrograph=river-1         ,reach-1         ,4400.00*
Stage Flow Hydrograph=river-1         ,reach-1         ,4300.00*
Stage Flow Hydrograph=river-1         ,reach-1         ,4200.00*
Stage Flow Hydrograph=river-1         ,reach-1         ,4100.00*
Stage Flow Hydrograph=river-1         ,reach-1         ,4000.00*
Stage Flow Hydrograph=river-1         ,reach-1         ,3900.00*
Stage Flow Hydrograph=river-1         ,reach-1         ,3800.00*
Stage Flow Hydrograph=river-1         ,reach-1         ,3700.00*
Stage Flow Hydrograph=river-1         ,reach-1         ,3600.00*
Stage Flow Hydrograph=river-1         ,reach-1         ,3500.00*
Stage Flow Hydrograph=river-1         ,reach-1         ,3400.00*
Stage Flow Hydrograph=river-1         ,reach-1         ,3300.00*
Stage Flow Hydrograph=river-1         ,reach-1         ,3200.00*
Stage Flow Hydrograph=river-1         ,reach-1         ,3100.00*
Stage Flow Hydrograph=river-1         ,reach-1         ,3000.00*
Stage Flow Hydrograph=river-1         ,reach-1         ,2900.00*
Stage Flow Hydrograph=river-1         ,reach-1         ,2800.00*
Stage Flow Hydrograph=river-1         ,reach-1         ,2700.00*
Stage Flow Hydrograph=river-1         ,reach-1         ,2600.00*
Stage Flow Hydrograph=river-1         ,reach-1         ,2500.00*
Stage Flow Hydrograph=river-1         ,reach-1         ,2400.00*
Stage Flow Hydrograph=river-1         ,reach-1         ,2300.00*
Stage Flow Hydrograph=river-1         ,reach-1         ,2200.00*
Stage Flow Hydrograph=river-1         ,reach-1         ,2100.00*
Stage Flow Hydrograph=river-1         ,reach-1         ,2000.00*
Stage Flow Hydrograph=river-1         ,reach-1         ,1900.00*
Stage Flow Hydrograph=river-1         ,reach-1         ,1800.00*
Stage Flow Hydrograph=river-1         ,reach-1         ,1700.00*
Stage Flow Hydrograph=river-1         ,reach-1         ,1600.00*
Stage Flow Hydrograph=river-1         ,reach-1         ,1500.00*
Stage Flow Hydrograph=river-1         ,reach-1         ,1400.00*
Stage Flow Hydrograph=river-1         ,reach-1         ,1300.00*
Stage Flow Hydrograph=river-1         ,reach-1         ,1200.00*
Stage Flow Hydrograph=river-1         ,reach-1         ,1100.00*
Stage Flow Hydrograph=river-1         ,reach-1         ,1000.00*
Stage Flow Hydrograph=river-1         ,reach-1         ,900.00*
Stage Flow Hydrograph=river-1         ,reach-1         ,800.00*
Stage Flow Hydrograph=river-1         ,reach-1         ,700.00*
Stage Flow Hydrograph=river-1         ,reach-1         ,600.00*
Stage Flow Hydrograph=river-1         ,reach-1         ,500.00*
Stage Flow Hydrograph=river-1         ,reach-1         ,400.00*
Stage Flow Hydrograph=river-1         ,reach-1         ,300.00*
Stage Flow Hydrograph=river-1         ,reach-1         ,200.00*
Stage Flow Hydrograph=river-1         ,reach-1         ,100.00*
Stage Flow Hydrograph=river-1         ,reach-1         ,0
Calibration Method= 0
Calibration Iterations= 20
Calibration Max Change=0.05
Calibration Tolerance=0.2
Calibration Maximum=1.5
Calibration Minimum=0.5
Calibration Optimization Method= 1
WQ AD Non Conservative
WQ ULTIMATE=-1
WQ Max Comp Step=1HOUR
WQ Output Interval=15MIN
WQ Output Selected Increments= 0
WQ Output face flow=0
WQ Output face velocity=0
WQ Output face area=0
WQ Output face dispersion=0
WQ Output cell volume=0
WQ Output cell surface area=0
WQ Output cell continuity=0
WQ Output cumulative cell continuity=0
WQ Output face conc=0
WQ Output face dconc_dx=0
WQ Output face courant=0
WQ Output face peclet=0
WQ Output face adv mass=0
WQ Output face disp mass=0
WQ Output cell mass=0
WQ Output cell source sink temp=0
WQ Output nsm pathways=0
WQ Output nsm derived pathways=0
WQ Output MaxMinRange=-1
WQ Daily Max Min Mean=-1
WQ Daily Range=0
WQ Daily Time=0
WQ Create Restart=0
WQ Fixed Restart=0
WQ System Summary=0
WQ Write To DSS=0
WQ Use Fixed Temperature=0
Sorting and Armoring Iterations= 10
XS Update Threshold= 0.02
Bed Roughness Predictor= 0
Hydraulics Update Threshold= 0.02
Energy Slope Method= 1
Volume Change Method= 1
Sediment Retention Method= 0
XS Weighting Method= 0
Number of US Weighted Cross Sections= 1
Number of DS Weighted Cross Sections= 1
Upstream XS Weight=0
Main XS Weight=1
Downstream XS Weight=0
Number of DS XS's Weighted with US Boundary= 1
Upstream Boundary Weight= 1
Weight of XSs Associated with US Boundary= 0
Number of US XS's Weighted with DS Boundary= 1
Downstream Boundary Weight= 0.5
Weight of XSs Associated with DS Boundary= 0.5
Percentile Method= 0
Sediment Output Level= 3
Mass or Volume Output= 0
Output Increment Type= 1
Profile and TS Output Increment= 1
XS Output Flag= 0
XS Output Increment= 10
Write Gradation File= 0
Read Gradation Hotstart= 0
Write HDF5 File= 1
Write Binary Output= 1
Write DSS Sediment File= 0
SV Curve= 0
Specific Gage Flag= 0

--- run_1_c6.u01 (unsteady flow) ---

Flow Title=flow_1
Program Version=5.05
Use Restart= 0
Initial Flow Loc=river-1         ,reach-1         ,10000   ,102
Boundary Location=river-1         ,reach-1         ,10000   ,        ,                ,                ,                ,
Interval=1HOUR
Stage Hydrograph= 361
    4.38    4.38    4.38    4.38    4.38    4.38    4.38    4.38    4.39    4.41
    4.45    4.56    4.76     5.1    5.61    6.29    7.15    8.16    9.28   10.46
   11.62   12.71   13.67   14.44   14.99   15.28   15.31    15.1   14.68   14.09
   13.38   12.58   11.75   10.92   10.11    9.36    8.65    8.01    7.43    6.92
    6.47    6.08    5.75    5.48    5.25    5.06    4.91    4.79    4.69    4.62
    4.56    4.51    4.48    4.45    4.43    4.42    4.41     4.4     4.4    4.39
    4.39    4.39    4.38    4.38    4.38    4.38    4.38    4.38    4.38    4.38
    4.38    4.38    4.38    4.38    4.38    4.38    4.38    4.38    4.38    4.38
    4.38    4.38    4.38    4.38    4.38    4.38    4.38    4.38    4.38    4.38
    4.38    4.38    4.38    4.38    4.38    4.38    4.38    4.38    4.38    4.38
    4.38    4.38    4.38    4.38    4.38    4.38    4.38    4.38    4.38    4.38
    4.38    4.38    4.38    4.38    4.38    4.38    4.38    4.38    4.38    4.38
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DSS File=stage_hydrograph_10000.dss
DSS Path=/RIVER-1/REACH-1/STAGE/01JUN2020/1HOUR/10000/
Use DSS=False
Use Fixed Start Time=False
Is Critical Boundary=False
Boundary Location=river-1         ,reach-1         ,0       ,        ,                ,                ,                ,
Friction Slope=0.0001,0
Boundary Location=river-1         ,reach-1         ,9500.00*,        ,                ,                ,                ,
Interval=1HOUR
Observed Stage and Flow Hydrograph= 0
DSS File=IB_conditions_stagehyd.dss
DSS Path=/RIVER-1/REACH-1/STAGE/01JUN2020/1HOUR/9500/
Use DSS=True
Use Fixed Start Time=False
Is Critical Boundary=False
Boundary Location=river-1         ,reach-1         ,9300.00*,        ,                ,                ,                ,
Interval=1HOUR
Observed Stage and Flow Hydrograph= 0
DSS File=IB_conditions_stagehyd.dss
DSS Path=/RIVER-1/REACH-1/STAGE/01JUN2020/1HOUR/9300/
Use DSS=True
Use Fixed Start Time=False
Is Critical Boundary=False
Boundary Location=river-1         ,reach-1         ,9000.00*,        ,                ,                ,                ,
Interval=1HOUR
Observed Stage and Flow Hydrograph= 0
DSS File=IB_conditions_stagehyd.dss
DSS Path=/RIVER-1/REACH-1/STAGE/01JUN2020/1HOUR/9000/
Use DSS=True
Use Fixed Start Time=False
Is Critical Boundary=False

--- run_1_c6.g01 (geometry) ---

Geom Title=geom_1
Program Version=5.05

River Reach=river-1         ,reach-1
Reach XY= 2
-0.32468879668050.863070539419091.106846473029050.28008298755187

Type RM Length L Ch R = 1 ,10000   ,100,100,100
BEGIN DESCRIPTION:
Upstream boundary
END DESCRIPTION:
#Sta/Elev= 4
       2      11       2       1      52       1      52      11
#Mann= 3 , 0 , 0
       2     .05       0       2     .03       0      52     .05       0
Bank Sta=2,52
XS Rating Curve= 0 ,0
Exp/Cntr=0.3,0.1

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
Type RM Length L Ch R = 1 ,0       ,,,
BEGIN DESCRIPTION:
Downstream boundary
END DESCRIPTION:
#Sta/Elev= 4
       2      10       2       0      52       0      52      10
#Mann= 3 , 0 , 0
       2     .05       0       2     .03       0      52     .05       0
Bank Sta=2,52
XS Rating Curve= 0 ,0
Exp/Cntr=0.3,0.1
LCMann Table=0

Chan Stop Cuts=-1
Use User Specified Reach Order=0
Composite Channel Slope=5